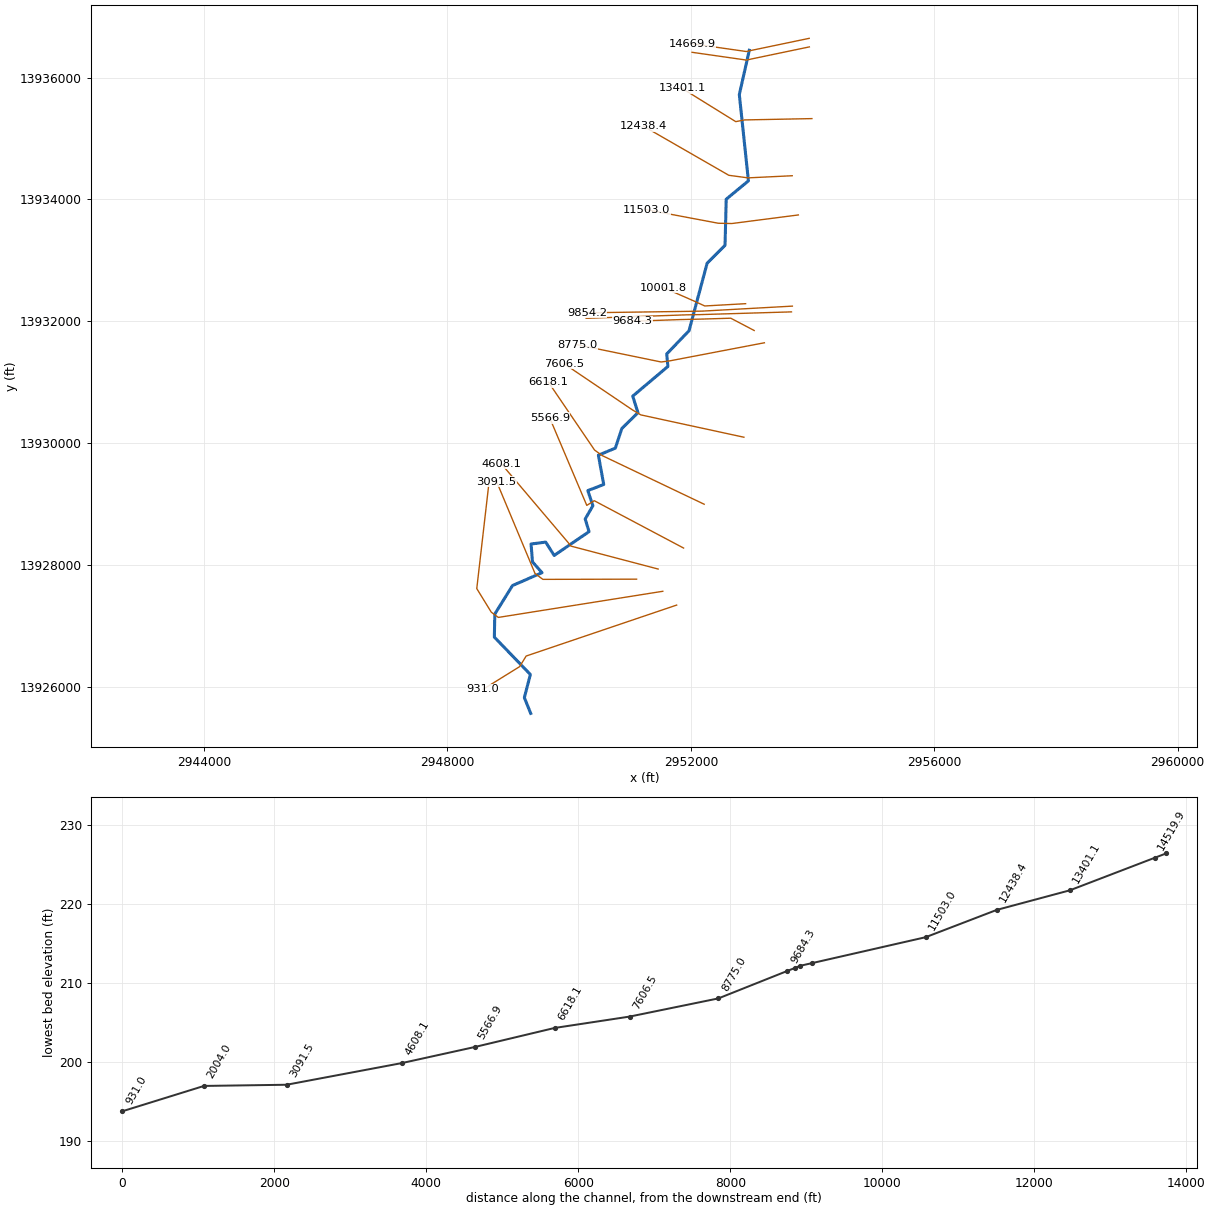
--- K166-02-00.prj (project) ---

Proj Title=K166-02-00
Current Plan=p02
Default Exp/Contr=.3,.1
English Units
Geom File=g01
Flow File=f01
Flow File=f04
Flow File=f02
Plan File=p01
Plan File=p04
Plan File=p02
Y Axis Title=Elevation
X Axis Title(PF)=Main Channel Distance
X Axis Title(XS)=Station
BEGIN DESCRIPTION:
Cypress Creek Watershed
Little Mound Creek
HCFCD Unit K166-02-00
Flood Hazard Model
10, 2, 1, 0.2%
Filename K166-02-00
Prepared by:  Halff Associates Inc  DATE:  March 24, 2004
Reviewed by:  _________  DATE:  __________________
STATUS (Final)
END DESCRIPTION:
DSS Export Rating Curves= 0
DSS Export Rating Curve Sorted= 0
DSS Export Volume Flow Curves= 0
DXF OffsetX= 0
DXF OffsetY= 0
DXF ScaleX= 1
DXF ScaleY= 10

--- K166-02-00.p02 (plan) ---

Plan Title=Floodway
Version=Version 3.0.1  Mar 2001
Short Identifier=Floodway0607
Geom File=g01
Flow File=f02
Subcritical Flow
K Sum by GR= 0
Std Step Tol= 0.01
Critical Tol= 0.01
Num of Std Step Trials= 20
Max Error Tol= 0.3
Flow Tol Ratio= 0.001
Split Flow NTrial= 30
Split Flow Tol= 0.02
Split Flow Ratio= 0.02
Log Output Level= 0
Friction Slope Method= 1
Unsteady Friction Slope Method= 2
Parabolic Critical Depth
Global Vel Dist= 0 , 0 , 0
Global Log Level= 0
CheckData=True
Encroach Param=-1 ,0,0, 3
Encroach River=K166-02-00
Encroach Reach=Reach - 1
Encroach Node=14669.9
       1 4982.54 5240.57       0       0       0
Encroach Node=14519.9
       1 4982.54 5240.57       1 4982.54 5240.57
Encroach Node=13401.1
       1  4877.6 5092.06       1  4877.6 5092.06
Encroach Node=12438.4
       1  4991.7 5298.67       1  4991.7 5298.67
Encroach Node=11503.0
       1 4835.02 5148.29       1 4835.02 5148.29
Encroach Node=10001.8
       1 4698.34 5224.23       0       0       0
Encroach Node=9854.2
       1 4698.34 5224.23       1 4698.34 5224.23
Encroach Node=9811.8
       1 4698.34 5224.23       1 4698.34 5224.23
Encroach Node=9784.3
       1 4698.34 5224.23       1 4698.34 5224.23
Encroach Node=9684.3
       1 4698.34 5224.23       0       0       0
Encroach Node=8775.0
       1  4819.3 5293.37       1  4819.3 5293.37
Encroach Node=7606.5
       1 4752.23 5158.21       1 4752.23 5158.21
Encroach Node=6618.1
       1 4631.25  5039.3       1 4631.25  5039.3
Encroach Node=5566.9
       1 4726.67 5121.18       4      .5
Encroach Node=4608.1
       1 4870.37 5309.72       4      .5
Encroach Node=3091.5
       1 4778.22 5149.81       4      .5
Encroach Node=2004.0
       1 4724.56 5091.98       1 4724.56 5091.98
Encroach Node=931.0
       1 4910.99  5468.2       1 4910.99  5468.2
Encroach Reach=K166-02-00_0009
Encroach Node=14669.9
       1 4982.54 5240.57       0       0       0
Encroach Node=14519.9
       1 4982.54 5240.57       0       0       0
Encroach Node=13401.1
       1  4877.6 5092.06       0       0       0
Encroach Node=12438.4
       1  4991.7 5298.67       0       0       0
Encroach Node=11503.0
       1 4835.02 5148.29       0       0       0
Encroach Node=10001.8
       1 4698.34 5224.23       0       0       0
Encroach Node=9854.2
       1 4698.34 5224.23       0       0       0
Encroach Node=9811.8
       1 4698.34 5224.23       0       0       0
Encroach Node=9784.3
       1 4698.34 5224.23       0       0       0
Encroach Node=9684.3
       1 4698.34 5224.23       0       0       0
Encroach Node=8775.0
       1  4819.3 5293.37       0       0       0
Encroach Node=7606.5
       1 4752.23 5158.21       0       0       0
Encroach Node=6618.1
       1 4631.25  5039.3       0       0       0
Encroach Node=5566.9
       1 4726.67 5121.18       0       0       0
Encroach Node=4608.1
       1 4870.37 5309.72       0       0       0
Encroach Node=3091.5
       1 4778.22 5149.81       0       0       0
Encroach Node=2004.0
       1 4724.56 5091.98       0       0       0
Encroach Node=931.0
       1 4910.99  5468.2       0       0       0
Computation Interval=1HOUR
Output Interval=1HOUR
Run HTab= 0
Run UNet= 0
Run PostProcess= 0
UNET Theta= 1
UNET ZTol= 0.02
UNET ZSATol= 0.1
UNET MxIter= 20
UNET MaxInSteps= 20
UNET DtIC= 0
UNET DtMin= 0
UNET MaxCRTS= 20
UNET WFStab= 2
UNET SFStab= 1
UNET WFX= 1
UNET SFX= 1
UNET Convert EG Bridges=-1
UNET Use Existing IB Tables=-1
Instantaneous Interval=1HOUR
Write IC File= 0
Write Velocity= 0
Write Detailed= 0

--- K166-02-00.p01 (plan) ---

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Plan Title=FEMA Effective June 2007
Short Identifier=FEMAeff0607
Geom File=g01
Flow File=f01
Encroach Param=-1 ,0,0, 0
IC Time=0

--- K166-02-00.p04 (plan) ---

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Plan Title=Storage Routing
Short Identifier=Store_Rout
Geom File=g01
Flow File=f04
Encroach Param=-1 ,0,0, 0

--- K166-02-00.f02 (steady flow) ---

Flow Title=Floodway
Version=Version 3.0.1  Mar 2001
Number of Profiles= 2
Profile Names=1PCT_100yr, 1PCTFloodway_100yrFW
River Rch & RM=K166-02-00,K166-02-00_0009,14669.9
    3910    3910
River Rch & RM=K166-02-00,K166-02-00_0009,13401.1
    4100    4100
River Rch & RM=K166-02-00,K166-02-00_0009,12438.4
    4380    4380
River Rch & RM=K166-02-00,K166-02-00_0009,11503.0
    4800    4800
River Rch & RM=K166-02-00,K166-02-00_0009,9854.2
    4930    4930
River Rch & RM=K166-02-00,K166-02-00_0009,8775.0
    5070    5070
River Rch & RM=K166-02-00,K166-02-00_0009,7606.5
    5200    5200
River Rch & RM=K166-02-00,K166-02-00_0009,6618.1
    5420    5420
River Rch & RM=K166-02-00,K166-02-00_0009,4608.1
    5590    5590
River Rch & RM=K166-02-00,K166-02-00_0009,3091.5
    5839    5839
Boundary for River Rch & Prof#=K166-02-00,K166-02-00_0009, 1
Up Type= 0
Dn Type= 3
Dn Slope=.0041
Boundary for River Rch & Prof#=K166-02-00,K166-02-00_0009, 2
Up Type= 0
Dn Type= 1
Dn Known WS=207.88
DSS Import GetInterval= 0
DSS Import GetPeak= 0
DSS Import FillOption= 0

--- K166-02-00.f01 (steady flow) ---

Flow Title=FEMA Effective June 2007
Version=Version 3.0.1  Mar 2001
Number of Profiles= 4
Profile Names=110PCT_10yr, 2PCT_50yr, 1PCT_100yr, 0.2PCT_500yr
River Rch & RM=K166-02-00,K166-02-00_0009,14669.9
    2060    3310    3910    5670
River Rch & RM=K166-02-00,K166-02-00_0009,13401.1
    2200    3500    4100    6000
River Rch & RM=K166-02-00,K166-02-00_0009,12438.4
    2270    3650    4380    6280
River Rch & RM=K166-02-00,K166-02-00_0009,11503.0
    2500    4000    4800    6900
River Rch & RM=K166-02-00,K166-02-00_0009,9854.2
    2580    4160    4930    7120
River Rch & RM=K166-02-00,K166-02-00_0009,8775.0
    2670    4340    5070    7380
River Rch & RM=K166-02-00,K166-02-00_0009,7606.5
    2750    4500    5200    7600
River Rch & RM=K166-02-00,K166-02-00_0009,6618.1
    2900    4660    5420    7860
River Rch & RM=K166-02-00,K166-02-00_0009,4608.1
    3020    4780    5590    8070
River Rch & RM=K166-02-00,K166-02-00_0009,3091.5
    3192    4960    5839    8373
Boundary for River Rch & Prof#=K166-02-00,K166-02-00_0009, 1
Up Type= 0
Dn Type= 3
Dn Slope=.0041
Boundary for River Rch & Prof#=K166-02-00,K166-02-00_0009, 2
Up Type= 0
Dn Type= 3
Dn Slope=.0041
Boundary for River Rch & Prof#=K166-02-00,K166-02-00_0009, 3
Up Type= 0
Dn Type= 3
Dn Slope=.0041
Boundary for River Rch & Prof#=K166-02-00,K166-02-00_0009, 4
Up Type= 0
Dn Type= 3
Dn Slope=.0041
DSS Import GetInterval= 0
DSS Import GetPeak= 0
DSS Import FillOption= 0

--- K166-02-00.f04 (steady flow) ---

Flow Title=Storage Routing
Version=Version 3.0.1  Mar 2001
Number of Profiles= 7
Profile Names=0.25*10% flood, 0.50*10%flood, 10% flood, 2% flood, 1% flood, 0.2%flood, 1.25*0.2% flood
River Rch & RM=K166-02-00,K166-02-00_0009,14669.9
      93     185     370     680     850    1040    1300
River Rch & RM=K166-02-00,K166-02-00_0009,12438.4
     113     225     450     820    1040    1280    1600
River Rch & RM=K166-02-00,K166-02-00_0009,11503
     135     270     540     970    1230    1520    1900
River Rch & RM=K166-02-00,K166-02-00_0009,8775
     150     300     600    1060    1360    1690    2113
River Rch & RM=K166-02-00,K166-02-00_0009,3091.5
     165     330     660    1160    1490    1860    2325
Boundary for River Rch & Prof#=K166-02-00,K166-02-00_0009, 1
Up Type= 0
Dn Type= 3
Dn Slope=.0041
Boundary for River Rch & Prof#=K166-02-00,K166-02-00_0009, 2
Up Type= 0
Dn Type= 3
Dn Slope=.0041
Boundary for River Rch & Prof#=K166-02-00,K166-02-00_0009, 3
Up Type= 0
Dn Type= 3
Dn Slope=.0041
Boundary for River Rch & Prof#=K166-02-00,K166-02-00_0009, 4
Up Type= 0
Dn Type= 3
Dn Slope=.0041
Boundary for River Rch & Prof#=K166-02-00,K166-02-00_0009, 5
Up Type= 0
Dn Type= 3
Dn Slope=.0041
Boundary for River Rch & Prof#=K166-02-00,K166-02-00_0009, 6
Up Type= 0
Dn Type= 3
Dn Slope=.0041
Boundary for River Rch & Prof#=K166-02-00,K166-02-00_0009, 7
Up Type= 0
Dn Type= 3
Dn Slope=.0041
DSS Import GetInterval= 0
DSS Import GetPeak= 0
DSS Import FillOption= 0

--- K166-02-00.g01 (geometry) ---

Geom Title=K166-02-00 June 2007
Version=Version 3.0.1  Mar 2001

River Reach=K166-02-00      ,K166-02-00_0009
Reach XY= 30
      2952960.54     13936448.17      2952796.75       13935721.
      2952946.15     13934303.89      2952581.15     13934002.69
      2952562.05     13933245.75      2952267.78     13932952.34
      2951970.09     13931843.13       2951603.7     13931461.79
      2951622.73     13931256.51      2951044.94     13930769.12
       2951130.8     13930497.68      2950866.17     13930237.56
      2950759.45     13929915.35      2950480.75      13929799.8
      2950568.44     13929318.53      2950306.73     13929217.93
      2950390.34      13928970.5      2950263.91     13928751.62
      2950327.12     13928544.29      2949754.09     13928153.43
      2949614.74     13928372.32      2949374.11     13928341.05
       2949397.9     13928047.39      2949554.24     13927869.98
      2949069.58     13927659.25      2948778.47     13927191.02
      2948771.09     13926812.28      2949362.75       13926199.
      2949264.25       13925819.      2949368.23      13925560.1

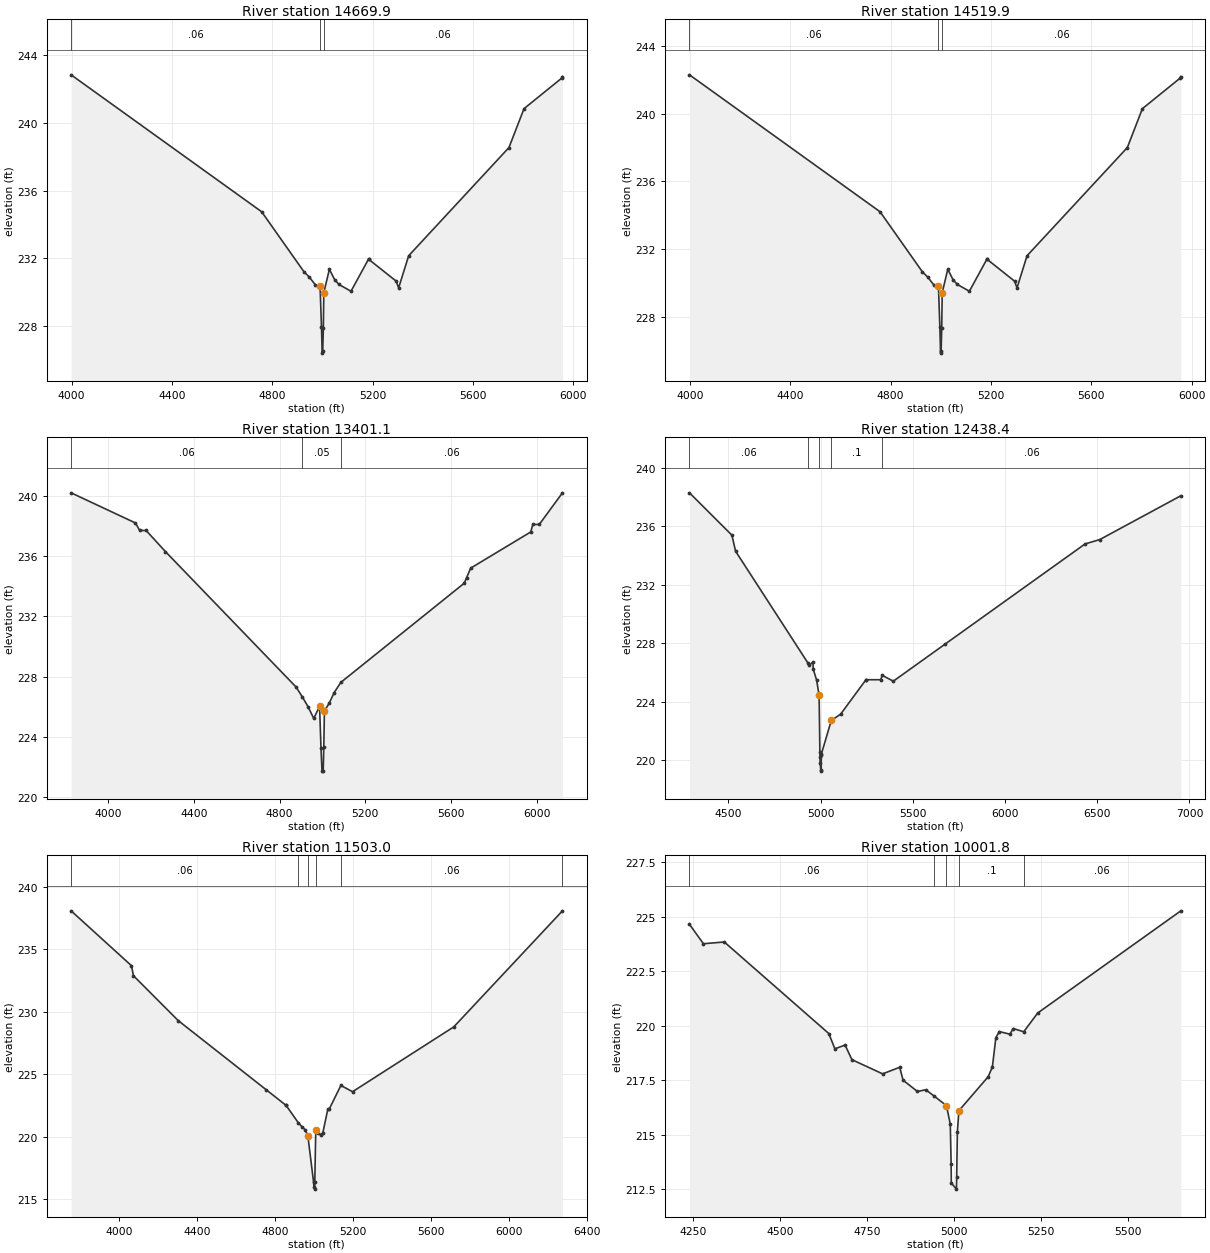
Type RM Length L Ch R = 1 ,14669.9 ,130,150,135
BEGIN DESCRIPTION:
Cross Section K166-02-00-X12a
END DESCRIPTION:
XS GIS Cut Line= 4
      2953944.74      13936644.5      2953024.08      13936452.6
      2952911.09       13936428.      2952016.85      13936555.7
#Sta/Elev= 24
  3997.8  242.85  4757.8  234.75    4926  231.21  4947.6  230.89  4971.8  230.43
  4990.6  230.34  4996.2  227.95    4999  226.39  5001.3  226.53  5003.7   227.9
  5005.5  229.96  5027.7  231.35  5048.9  230.73  5066.1  230.45  5113.9  230.05
  5183.9  231.95  5185.3  231.93  5293.9  230.65  5303.9  230.25  5343.9  232.15
  5743.9  238.55  5803.9  240.85  5953.9  242.65  5957.2  242.75
#Mann= 3 ,-1 , 0
  3997.8     .06       0  4990.6     .05       0  5005.5     .06       0
Bank Sta=4990.6,5005.5
XS Rating Curve= 0
Exp/Cntr=.3,.1

Type RM Length L Ch R = 1 ,14519.9 ,1025,1118.8,982
BEGIN DESCRIPTION:
Cross Section K166-02-00-X12
END DESCRIPTION:
XS GIS Cut Line= 4
      2953947.75       13936504.      2953027.09     13936312.05
       2952914.1     13936287.49      2952019.86     13936415.17
#Sta/Elev= 24
  3997.8   242.3  4757.8   234.2    4926  230.66  4947.6  230.34  4971.8  229.88
  4990.6  229.79  4996.2   227.4    4999  225.84  5001.3  225.98  5003.7  227.35
  5005.5  229.41  5027.7   230.8  5048.9  230.18  5066.1   229.9  5113.9   229.5
  5183.9   231.4  5185.3  231.38  5293.9   230.1  5303.9   229.7  5343.9   231.6
  5743.9     238  5803.9   240.3  5953.9   242.1  5957.2   242.2
#Mann= 3 ,-1 , 0
  3997.8     .06       0  4990.6     .05       0  5005.5     .06       0
Bank Sta=4990.6,5005.5
XS Rating Curve= 0
Exp/Cntr=.3,.1

Type RM Length L Ch R = 1 ,13401.1 ,955.03,962.7,933.03
BEGIN DESCRIPTION:
Cross Section K166-02-00-X11
END DESCRIPTION:
XS GIS Cut Line= 4
      2953989.33     13935326.48      2952883.45     13935304.74
      2952737.86     13935276.65      2951855.42     13935823.57
#Sta/Elev= 25
  3827.6   240.2  4127.6   238.2  4147.6   237.7  4177.6   237.7  4267.6   236.3
  4877.6   227.3  4907.2  226.63  4932.8  226.01  4959.6  225.22  4986.9  226.02
  4993.5  223.27  4998.2  221.72  5003.9  221.72  5006.6  223.33  5009.5  225.71
  5031.7  226.23  5055.3  226.94  5085.9  227.61    5662   234.2  5672.7  234.56
    5692   235.2    5972   237.6    5982   238.1    6012   238.1  6120.2   240.2
#Mann= 3 ,-1 , 0
  3827.6     .06       0  4907.2     .05       0  5085.9     .06       0
Bank Sta=4986.9,5009.5
XS Rating Curve= 0
Exp/Cntr=.3,.1

Type RM Length L Ch R = 1 ,12438.4 ,867.3,935.4,832
BEGIN DESCRIPTION:
Cross Section K166-02-00-X10
Deleted bad survey point (5003.2,223.1). Does not show up in photos. - JJA 3/17/03
END DESCRIPTION:
XS GIS Cut Line= 4
       2953666.3     13934388.33      2952940.04     13934353.33
      2952624.63     13934395.48      2951220.69     13935202.48
#Sta/Elev= 27
  4288.7   238.3  4518.7   235.4  4538.7   234.3  4931.8  226.63  4938.7   226.5
  4958.7   226.7  4959.5  226.24  4977.9  225.48  4991.7  224.44  4995.8  220.52
  4996.7   220.2    4997  219.77  5001.7  219.24    5003  219.32  5003.3  220.33
  5003.7   220.4  5057.6  222.71  5108.3  223.14  5245.7   225.5  5245.8   225.5
  5325.8   225.5    5334   225.8    5394   225.4  5674.9  227.94    6434   234.8
    6514   235.1  6953.4   238.1
#Mann= 5 ,-1 , 0
  4288.7     .06       0  4931.8      .1       0  4991.7     .06       0
  5057.6      .1       0    5334     .06       0
Bank Sta=4991.7,5057.6
XS Rating Curve= 0
Exp/Cntr=.3,.1

Type RM Length L Ch R = 1 ,11503.0 ,1416.8,1501.2,1574.8
BEGIN DESCRIPTION:
Cross Section K166-02-00-X9
END DESCRIPTION:
XS GIS Cut Line= 4
      2953767.28     13933744.58       2952672.3     13933603.46
      2952451.37     13933608.21      2951274.34     13933829.78
#Sta/Elev= 25
    3752   238.1    4062   233.7    4072   232.9    4302   229.3  4752.6  223.77
  4855.9   222.5    4856   222.5  4918.1  221.12    4938  220.78  4953.5  220.55
  4967.5  220.06  4996.9  216.35  4998.8  215.95  5002.5  215.79  5003.1  216.39
  5008.1  220.49  5019.8  220.27  5033.1  220.15  5044.6  220.32    5070   222.2
    5077   222.2    5137   224.1    5197   223.6    5717   228.8  6274.7   238.1
#Mann= 6 ,-1 , 0
    3752     .06       0  4918.1      .1       0  4967.5     .08       0
  5008.1      .1       0    5137     .06       0  6274.7     .99       0
Bank Sta=4967.5,5008.1
XS Rating Curve= 0
Exp/Cntr=.3,.1

Type RM Length L Ch R = 1 ,10001.8 ,232,147.6,74
BEGIN DESCRIPTION:
S1_Betka - XS 4
LIDAR overbanks, Interpolated channel
END DESCRIPTION:
XS GIS Cut Line= 4
      2952899.72     13932287.47      2952228.56     13932249.85
      2952049.07     13932332.36      2951553.26     13932549.43
#Sta/Elev= 30
  4240.1  224.65  4280.1  223.76  4340.1  223.84  4640.1  219.64 4657.58  218.94
 4686.96  219.11 4706.55  218.44  4794.7  217.79 4843.68  218.09 4853.47   217.5
 4894.61  216.98 4918.61  217.06 4941.82  216.78 4978.06  216.33    4989  215.48
 4991.46  213.64 4991.97  212.78 5006.69   212.5 5007.37  213.04 5009.33  215.13
 5013.74   216.1 5097.95  217.66  5109.9  218.11  5119.9  219.45  5129.9  219.73
  5159.9  219.61  5169.9  219.87  5199.9  219.72  5239.9  220.58  5651.1  225.27
#Mann= 5 ,-1 , 0
  4240.1     .06       0 4941.82      .1       0 4978.06     .08       0
 5013.74      .1       0  5199.9     .06       0
Bank Sta=4978.06,5013.74
XS Rating Curve= 0
Exp/Cntr=.5,.3

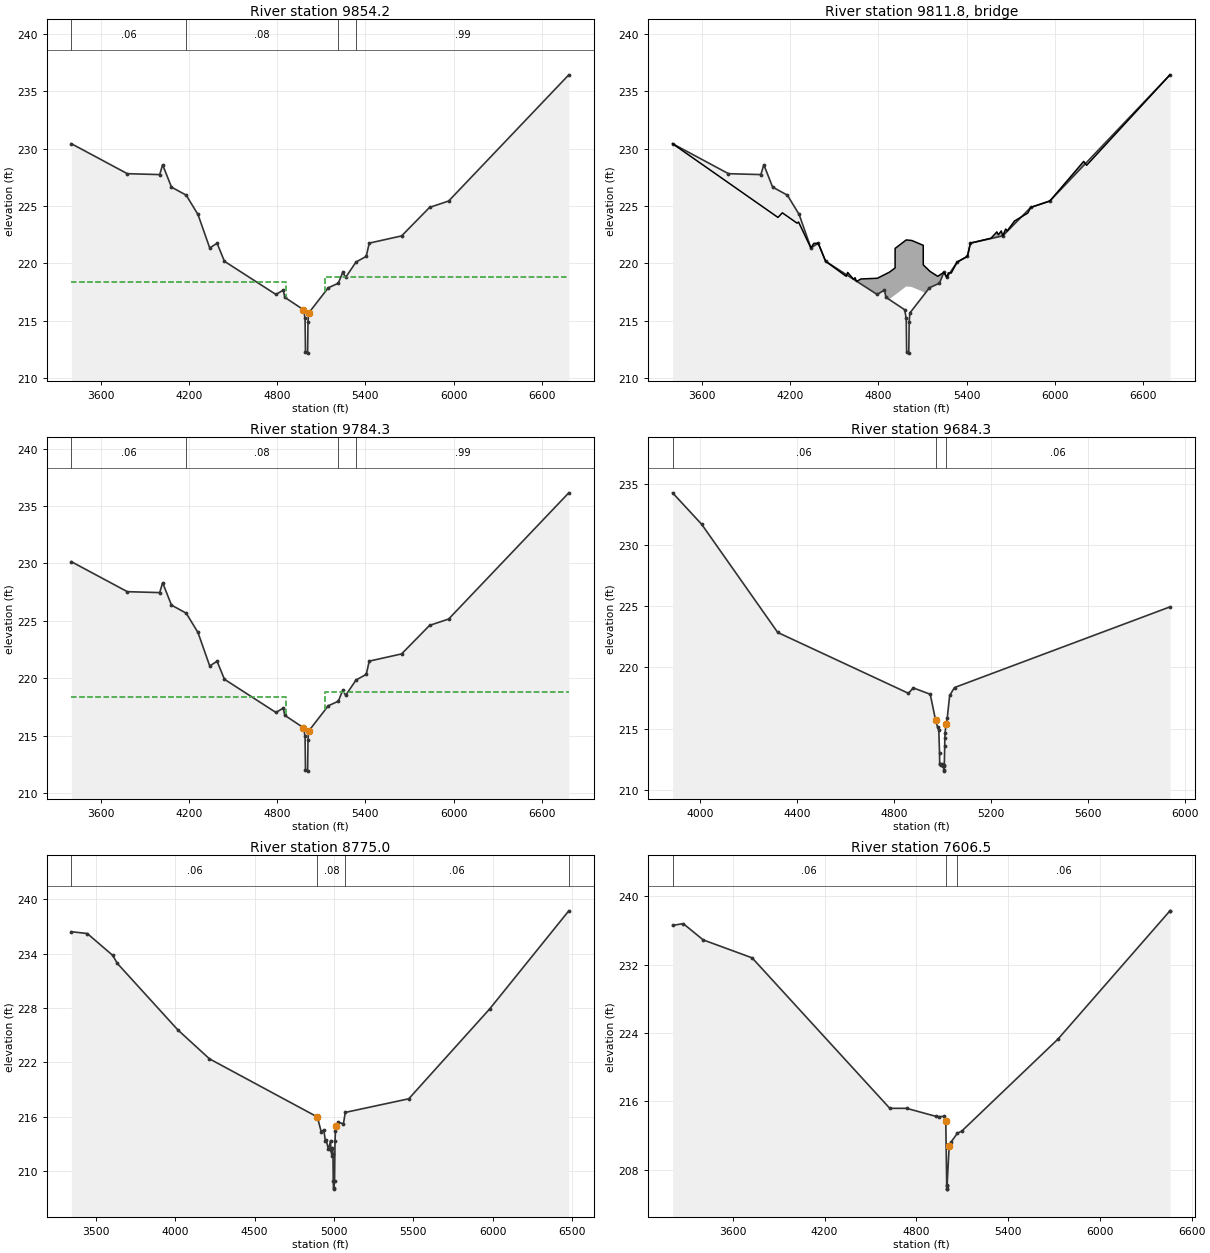
Type RM Length L Ch R = 1 ,9854.2  ,69.9,69.9,69.9
BEGIN DESCRIPTION:
S1_Betka - XS 3
END DESCRIPTION:
XS GIS Cut Line= 4
      2953668.76      13932247.4      2952189.45     13932165.33
      2951967.22     13932161.47      2950291.06      13932137.8
#Sta/Elev= 30
  3401.9  230.42  3781.9  227.81  4001.9  227.73  4021.9  228.59  4081.9  226.64
  4181.9  225.94  4261.9  224.26  4341.9  221.34  4391.9  221.75  4441.9  220.18
  4791.9  217.29  4841.9  217.67  4851.9  217.04  4979.1  215.96  4989.8   215.2
  4992.7  212.27  5007.1  212.18  5009.8  214.89  5014.3  215.67  5147.5  217.87
  5215.8  218.27  5245.8  219.22  5265.8  218.78  5335.8  220.11  5405.8  220.61
  5425.8  221.76  5645.8  222.39  5835.8  224.87  5965.8  225.43  6782.1  236.42
#Mann= 4 ,-1 , 0
  3401.9     .06       0  4181.9     .08       0  5215.8     .06       0
  5335.8     .99       0
#XS Ineff= 2 , 0
       0    4863   218.4    5124       0   218.8
Permanent Ineff=
       F       F
Bank Sta=4979.1,5014.3
XS Rating Curve= 0
Exp/Cntr=.5,.3

Type RM Length L Ch R = 3 ,9811.8  ,,,
BEGIN DESCRIPTION:
BETKA
Structure ID: K166-02-00-S1
END DESCRIPTION:
Bridge Culvert--1,0,-1,-1, 0
Deck Dist Width WeirC Skew NumUp NumDn MinLoCord MaxHiCord MaxSubmerge Is_Ogee
10,42,2.6,0, 48, 49, , , .95, 0, ,,,
  3401.9    4118    4148    4248    4258  4341.9  4361.9  4391.9  4441.9  4581.9
  4591.9  4631.9  4641.9  4651.9  4681.9  4793.3 4875.43  4875.5 4914.09  4914.2
  4989.8  5027.5  5105.5 5105.61    5115  5151.3  5203.9  5245.8  5265.8  5275.8
  5295.8  5335.8  5405.8  5425.8  5565.8  5605.8  5615.8  5635.8  5645.8  5665.8
  5675.8  5725.8  5815.8  5835.8  5965.8  6195.8  6215.8  6782.1
  230.42     224   224.4   223.5   223.6  221.34  221.74  221.75  220.18  218.87
  219.21  218.61  218.75  218.42  218.64   218.7  219.23  219.23   219.6   221.3
  222.04  221.99  221.57  219.87  219.75   219.3  218.87  219.22  218.78  219.17
  219.16  220.11  220.61  221.76  222.19  222.74  222.49  222.82  222.39  222.99
  222.82  223.69  224.38  224.87  225.43  228.88  228.54  236.42
     216     216     216     216     216     216     216     216     216     216
     216     216     216     216     216     216     216  216.88  217.25  217.25
  217.99  217.94  217.52  217.52  217.39  217.89     216     216     216     216
     216     216     216     216     216     216     216     216     216     216
     216     216     216     216     216     216     216     216
  3401.9    4118    4148    4248    4258  4341.9  4361.9  4391.9  4441.9  4581.9
  4591.9  4631.9  4641.9  4651.9  4681.9  4793.3 4875.43  4875.5 4914.09  4914.2
  4989.8  5027.5  5105.5 5105.61 5114.89    5115  5151.3  5203.9  5245.8  5265.8
  5275.8  5295.8  5335.8  5405.8  5425.8  5565.8  5605.8  5615.8  5635.8  5645.8
  5665.8  5675.8  5725.8  5815.8  5835.8  5965.8  6195.8  6215.8  6782.1
  230.42     224   224.4   223.5   223.6  221.34  221.74  221.75  220.18  218.87
  219.21  218.61  218.75  218.42  218.64   218.7  219.23  219.23   219.6   221.3
  222.04  221.99  221.57  219.87  219.75  219.75   219.3  218.87  219.22  218.78
  219.17  219.16  220.11  220.61  221.76  222.19  222.74  222.49  222.82  222.39
  222.99  222.82  223.69  224.38  224.87  225.43  228.88  228.54  236.42
     216     216     216     216     216     216     216     216     216     216
     216     216     216     216     216     216     216  216.88  217.25  217.25
  217.99  217.94  217.52  217.52   217.4     216     216     216     216     216
     216     216     216     216     216     216     216     216     216     216
     216     216     216     216     216     216     216     216     216
BR Coef= 1 , 1 , 0 ,1.25, 0 ,,,.8,0,2,0,
WSPro=,,,, 1 ,,,, 0 ,,,, 0 ,,,,-1 ,-1 ,-1 , 0 , 0 , 0 , 0 , 0
BC Design=,, 0 ,, 0 ,,,,,,
BC HTab HWMax=236.42

Type RM Length L Ch R = 1 ,9784.3  ,82,100,84
BEGIN DESCRIPTION:
S1_Betka - XS 2
END DESCRIPTION:
XS GIS Cut Line= 5
      2953653.81      13932152.8      2952152.85     13932108.01
      2951928.87     13932104.12     2950315.641    13932048.531
     2950279.042     13932048.51
#Sta/Elev= 30
  3401.9  230.15  3781.9  227.54  4001.9  227.46  4021.9  228.32  4081.9  226.37
  4181.9  225.67  4261.9  223.99  4341.9  221.07  4391.9  221.48  4441.9  219.91
  4791.9  217.02  4841.9   217.4  4851.9  216.77  4979.1  215.69  4989.8  214.93
  4992.7     212  5007.1  211.91  5009.8  214.62  5014.3   215.4  5147.5   217.6
  5215.8     218  5245.8  218.95  5265.8  218.51  5335.8  219.84  5405.8  220.34
  5425.8  221.49  5645.8  222.12  5835.8   224.6  5965.8  225.16  6782.1  236.15
#Mann= 4 ,-1 , 0
  3401.9     .06       0  4181.9     .08       0  5215.8     .06       0
  5335.8     .99       0
#XS Ineff= 2 , 0
       0    4863   218.4    5124       0   218.8
Permanent Ineff=
       F       F
Bank Sta=4979.1,5014.3
XS Rating Curve= 0
Exp/Cntr=.5,.3

Type RM Length L Ch R = 1 ,9684.3  ,927.3,909.3,925.3
BEGIN DESCRIPTION:
S1_Betka - XS 1
LIDAR overbanks, Interpolated channel
END DESCRIPTION:
XS GIS Cut Line= 5
      2953040.61     13931847.32      2952656.36     13932048.89
      2952157.38     13932033.99      2951845.95     13932027.05
      2951039.05     13931999.28
#Sta/Elev= 29
  3886.1  234.27  4006.1   231.7    4320  222.86  4859.2  217.89  4879.2  218.33
  4949.2  217.81 4970.82  215.72 4979.42  215.12  4984.4  214.89 4987.44  213.01
 4988.08  212.14 4988.13  212.13 4994.65  212.01 4999.32  212.09 4999.77  211.99
 5002.09  211.91 5003.35  211.99 5004.48  211.92 5005.13  211.62 5006.36  211.53
 5007.13  212.03 5008.83  213.62 5009.32   214.2 5010.37  214.64 5014.27  215.36
  5019.2  215.85  5029.2  217.71  5049.2  218.36  5938.1  224.95
#Mann= 3 ,-1 , 0
  3886.1     .06       0 4970.82     .08       0 5014.27     .06       0
Bank Sta=4970.82,5014.27
XS Rating Curve= 0
Exp/Cntr=.3,.1

Type RM Length L Ch R = 1 ,8775.0  ,1169.5,1168.5,820
BEGIN DESCRIPTION:
Cross Section K166-02-00-X8
END DESCRIPTION:
XS GIS Cut Line= 4
      2953208.64      13931645.6      2951654.81     13931348.63
       2951511.7     13931330.08      2950132.05     13931613.49
#Sta/Elev= 30
  3345.6   236.4  3445.6   236.2  3605.6   233.8  3635.6   232.9  4015.6   225.6
  4215.6   222.4  4895.5     216  4920.7  214.33  4936.3  214.59  4946.2  213.35
  4951.8  213.43  4965.3  212.42    4979  213.39  4980.3  212.41  4987.1  211.73
  4990.8  212.62  4994.1  211.91    4996   208.9  4997.5  208.18  4999.6  208.05
  5004.1  208.99  5006.9  213.37  5009.9   214.5    5014     215  5026.1   215.4
  5060.1  215.26  5071.8   216.5  5471.9     218  5981.9   227.9  6480.3   238.7
#Mann= 4 ,-1 , 0
  3345.6     .06       0  4895.5     .08       0  5071.8     .06       0
  6480.3     .99       0
Bank Sta=4895.5,5014
XS Rating Curve= 0
Exp/Cntr=.3,.1

Type RM Length L Ch R = 1 ,7606.5  ,961.22,988.4,934.96
BEGIN DESCRIPTION:
Cross Section K166-02-00-X7
END DESCRIPTION:
XS GIS Cut Line= 4
      2952872.58     13930094.55      2951177.35     13930461.47
      2951044.22     13930540.83      2949915.19     13931302.52
#Sta/Elev= 21
  3206.7   236.6  3276.7   236.8  3406.7   234.9  3726.7   232.8  4626.7   215.2
  4736.7   215.2  4926.3  214.27  4951.4  214.22    4979  214.27  4992.6  213.69
  4998.8  206.13  4999.4  205.77  5000.5  205.75  5001.2  206.18  5014.8  210.77
  5028.1  211.27  5067.9  212.28  5097.1  212.54  5726.2   223.3    6458   238.3
  6458.1   238.3
#Mann= 3 ,-1 , 0
  3206.7     .06       0  4992.6     .08       0  5067.9     .06       0
Bank Sta=4992.6,5014.8
XS Rating Curve= 0
Exp/Cntr=.3,.1

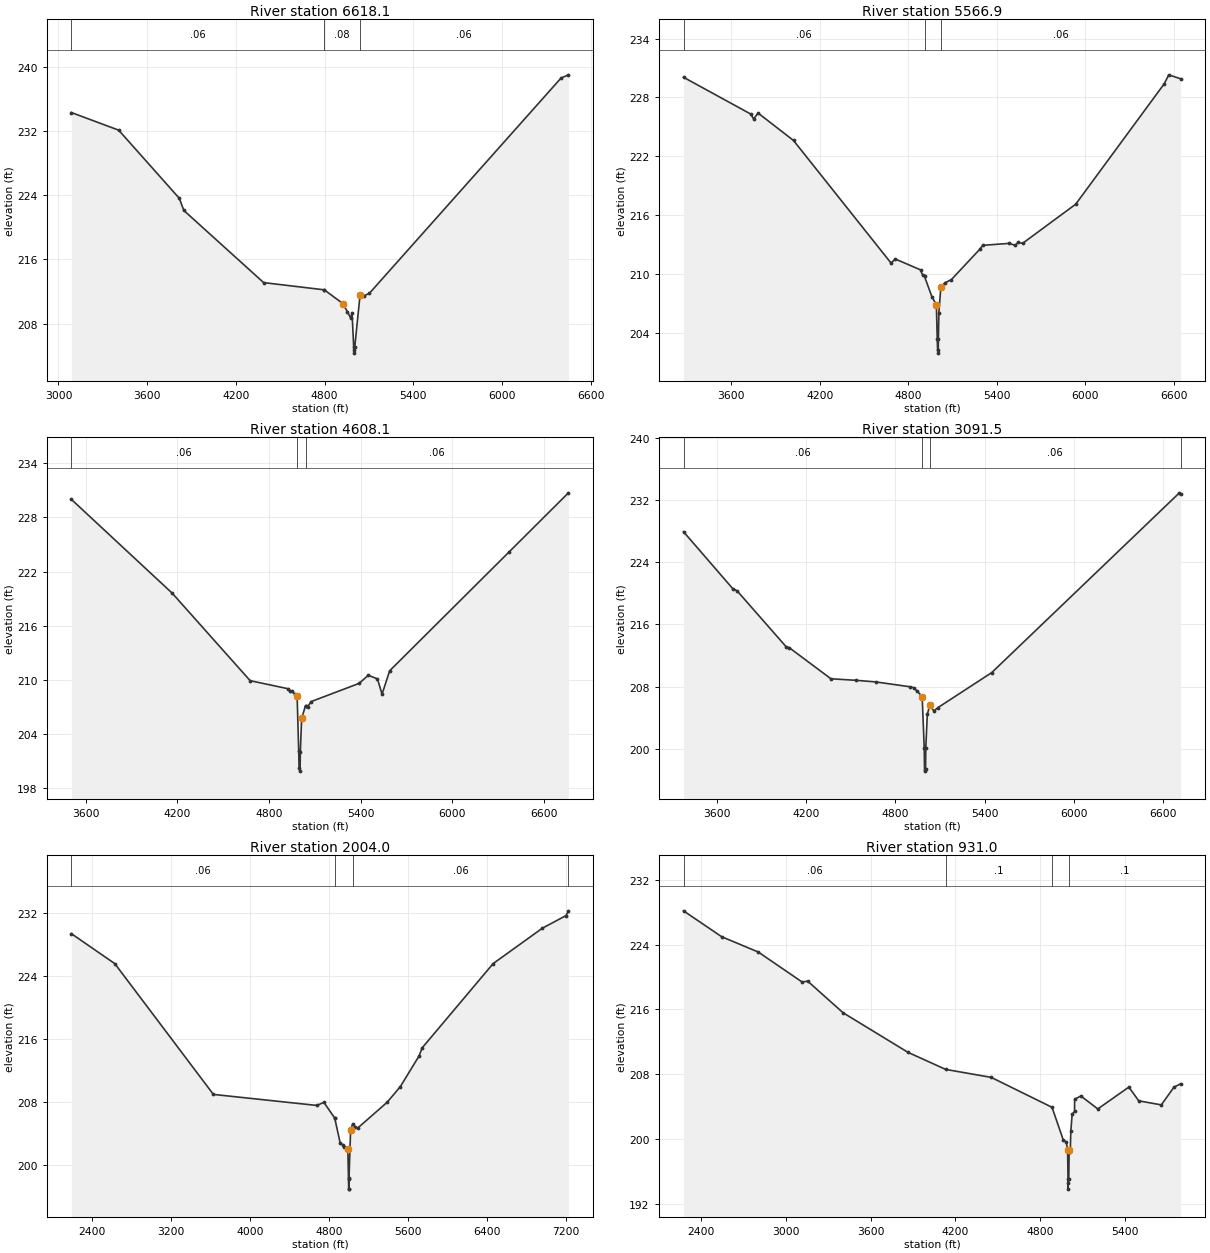
Type RM Length L Ch R = 1 ,6618.1  ,899.87,1051.2,1008.42
BEGIN DESCRIPTION:
Cross Section K166-02-00-X06
END DESCRIPTION:
XS GIS Cut Line= 4
      2952218.82      13928994.3      2950545.48     13929792.06
      2950417.91     13929883.91      2949658.59       13931000.
#Sta/Elev= 20
  3087.5   234.3  3407.5   232.1  3817.5   223.6  3847.5   222.1  4387.5   213.1
  4797.4   212.2  4797.5   212.2  4924.4  210.47  4953.9  209.46    4976  208.69
  4985.3  209.35  4996.2  205.13  4997.5  204.68  5001.2  204.31  5003.8  205.13
  5039.3  211.54  5066.5  211.45  5102.3  211.76  6398.5   238.6  6448.5     239
#Mann= 3 ,-1 , 0
  3087.5     .06       0  4797.4     .08       0  5039.3     .06       0
Bank Sta=4924.4,5039.3
XS Rating Curve= 0
Exp/Cntr=.3,.1

Type RM Length L Ch R = 1 ,5566.9  ,957.8,958.8,959.8
BEGIN DESCRIPTION:
Cross Section K166-02-00-X5
END DESCRIPTION:
XS GIS Cut Line= 4
      2951880.71      13928274.8      2950412.46     13929052.24
       2950289.9     13928975.14      2949680.96      13930411.4
#Sta/Elev= 30
  3277.7  230.05  3732.7   226.3  3752.7   225.8  3782.7   226.4  4022.7   223.6
  4682.7   211.1  4712.7   211.5  4882.7   210.4  4897.1  209.85  4910.1  209.72
  4960.1  207.64  4990.1  206.84  4996.1   203.3  4998.4  202.18    5003   201.9
  5003.9  203.34    5007  206.02  5020.5  208.64  5047.5  209.07  5091.6   209.4
  5283.9   212.5  5303.9   212.9  5483.9   213.1  5523.9   212.9  5543.9   213.2
  5573.9   213.1  5933.9   217.1  6533.9   229.4  6563.9   230.3  6643.9   229.9
#Mann= 3 ,-1 , 0
  3277.7     .06       0  4910.1     .05       0  5020.5     .06       0
Bank Sta=4990.1,5020.5
XS Rating Curve= 0
Exp/Cntr=.3,.1

Type RM Length L Ch R = 1 ,4608.1  ,1463.27,1516.6,1290.88
BEGIN DESCRIPTION:
Cross Section K166-02-00-X4
END DESCRIPTION:
XS GIS Cut Line= 4
      2951462.83      13927930.1       2950029.1     13928306.92
      2949979.16     13928370.36       2948885.4      13929658.6
#Sta/Elev= 24
    3507     230    4167   219.6    4677   209.9    4927     209  4934.8   208.8
  4948.2  208.75  4967.6  208.44  4984.3  208.24  4994.6   202.1  4997.2  200.18
  5003.6  199.87  5005.4  202.01  5013.9  205.71  5039.3  207.13  5039.4  207.13
  5052.6  206.99  5075.8  207.58  5390.1   209.6  5450.1   210.5  5510.1   210.1
  5540.1   208.4  5590.1     211  6370.1  224.15  6760.1  230.73
#Mann= 3 ,-1 , 0
    3507     .06       0  4984.3     .05       0  5039.3     .06       0
Bank Sta=4984.3,5013.9
XS Rating Curve= 0
Exp/Cntr=.3,.1

Type RM Length L Ch R = 1 ,3091.5  ,520,1087.5,992.68
BEGIN DESCRIPTION:
Cross Section K166-02-00-X3
END DESCRIPTION:
XS GIS Cut Line= 4
      2951108.43      13927763.8      2949568.83     13927760.49
      2949439.75     13927856.01       2948807.6     13929366.95
#Sta/Elev= 23
  3378.2   227.9  3708.2   220.6  3738.2   220.3  4068.2   213.1  4088.2     213
  4368.2     209  4538.2   208.8  4668.2   208.6    4900  207.97  4923.3  207.86
  4947.2  207.41    4981  206.72  4994.8  200.09  4996.9  197.13  5003.8  197.38
  5005.2   200.1  5015.6  204.44  5031.6  205.57  5059.9  204.87  5087.4   205.3
  5448.4   209.8  6708.4   232.9  6716.2   232.8
#Mann= 4 ,-1 , 0
  3378.2     .06       0    4981     .05       0  5031.6     .06       0
  6716.2     .99       0
Bank Sta=4981,5031.6
XS Rating Curve= 0
Exp/Cntr=.3,.1

Type RM Length L Ch R = 1 ,2004.0  ,830.64,1073,1420
BEGIN DESCRIPTION:
Cross Section K166-02-00-X2
END DESCRIPTION:
XS GIS Cut Line= 5
      2951539.27       13927565.      2948836.27      13927135.7
      2948720.46     13927221.94      2948482.08     13927609.14
      2948677.39     13929301.85
#Sta/Elev= 27
  2187.6   229.4  2627.6   225.6  3627.6     209  4677.6   207.6  4747.6     208
  4857.5     206  4857.6     206  4912.2  202.89  4938.4   202.6  4954.9  202.33
  4990.4  202.05  4997.5  198.24  4999.4  196.99  5000.7  196.98  5002.5  198.35
  5018.9   204.5  5040.2  205.27  5065.4  204.86  5090.5  204.73    5389     208
  5523.7     210  5713.7   213.9  5743.7   214.9  6463.7   225.6  6963.7   230.1
  7203.7   231.7  7227.6   232.3
#Mann= 4 ,-1 , 0
  2187.6     .06       0  4857.5    .045       0  5040.2     .06       0
  7227.6     .99       0
Bank Sta=4990.4,5018.9
XS Rating Curve= 0
Exp/Cntr=.3,.1

Type RM Length L Ch R = 1 ,931.0   ,0,0,0
BEGIN DESCRIPTION:
Cross Section K166-02-00-X1
END DESCRIPTION:
XS GIS Cut Line= 4
      2951766.72      13927338.4      2949293.69     13926501.62
      2949186.57     13926327.71      2948586.24     13925955.49
#Sta/Elev= 30
  2273.2   228.2  2543.2     225  2803.2   223.1  3113.2   219.4  3153.2   219.5
  3403.2   215.6  3863.2   210.7  4130.2  208.59  4453.2   207.6  4883.9   203.9
  4963.5  199.87    4985  199.57  4994.3  198.67  4997.3  195.06  4997.4  193.78
  4998.7  194.55  5002.6  195.02  5005.3  198.65  5013.2  198.38  5017.1  200.94
  5026.5  203.02  5043.5   203.4    5044   204.9  5088.3   205.3  5208.3   203.7
  5428.3   206.4  5498.3   204.7  5658.3   204.2  5748.3   206.4  5794.6   206.8
#Mann= 4 ,-1 , 0
  2273.2     .06       0  4130.2      .1       0  4883.9     .08       0
  5005.3      .1       0
Bank Sta=4994.3,5005.3
XS Rating Curve= 0
Exp/Cntr=.3,.1

Chan Stop Cuts=-1